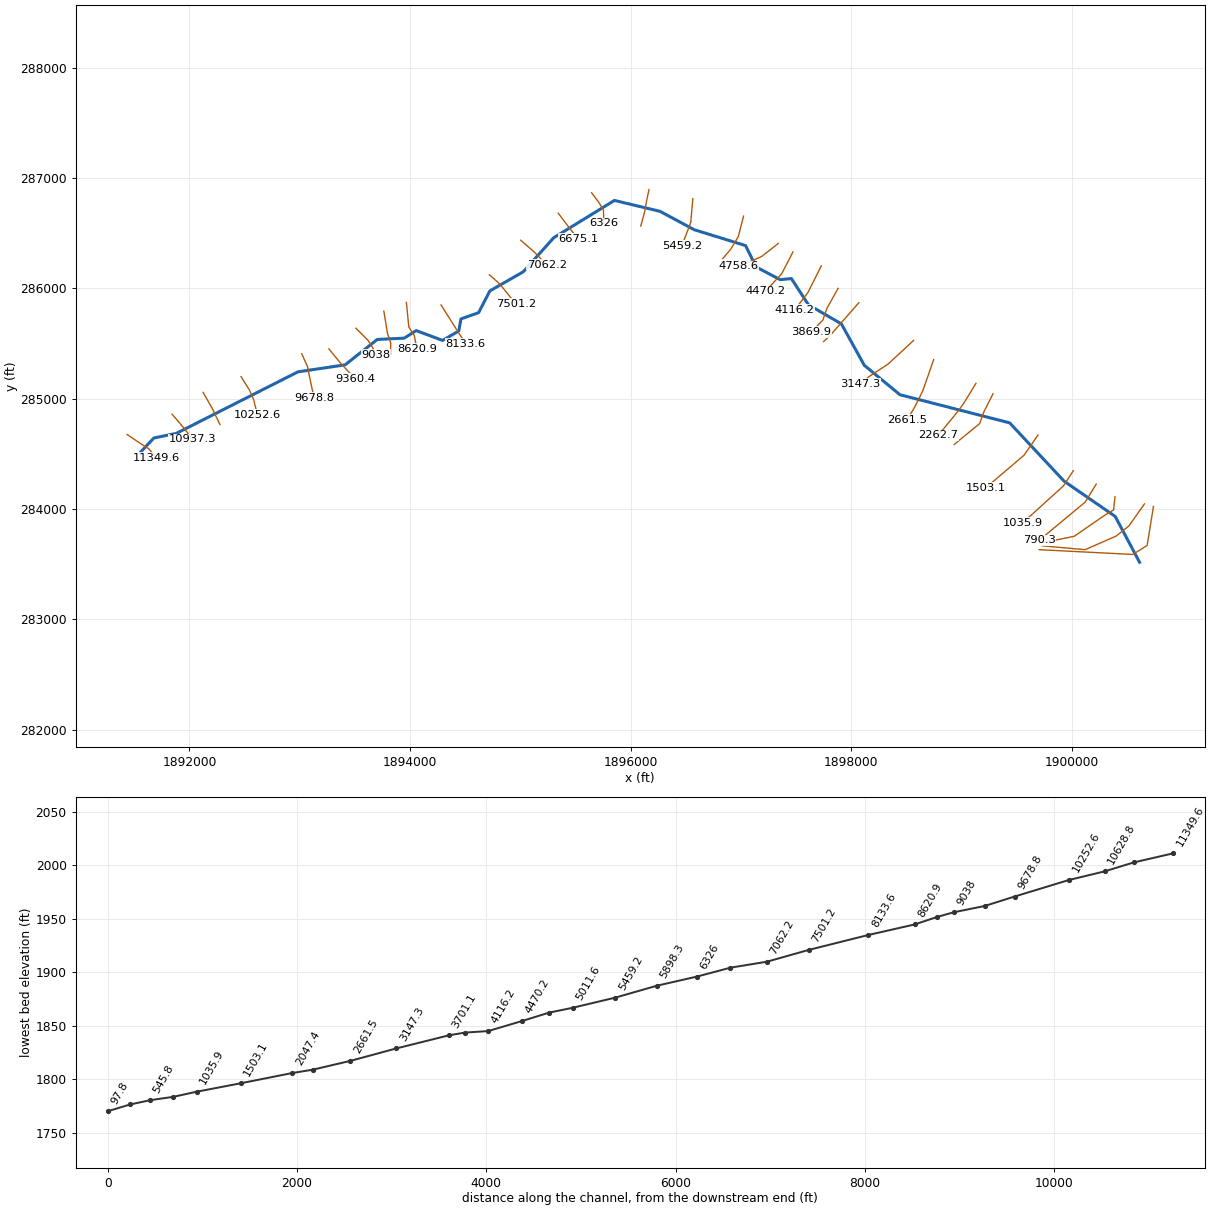
--- NP1.prj (project) ---

Proj Title=NP1
Current Plan=p01
Default Exp/Contr=0,0
English Units
Geom File=g01
Flow File=f01
Plan File=p01
BEGIN DESCRIPTION:
END DESCRIPTION:
DSS Export Rating Curves= 0
DSS Export Rating Curve Sorted= 0
DSS Export Volume Flow Curves= 0
DXF OffsetX= 0
DXF OffsetY= 0
DXF ScaleX= 0
DXF ScaleY= 0

--- NP1.p01 (plan) ---

Plan Title=Floodplain
Program Version=4.00
Geom File=g01
Flow File=f01
K Sum by GR=0
Std Step Tol=0.01
Critical Tol=0.01
Num of Std Step Trials=20
Max Error Tol=0.3
Flow Tol Ratio=0.001
Split Flow NTrial=30
Split Flow Tol=0.02
Split Flow Ratio=0.02
Log Output Level=0
Friction Slope Method=1
Unsteady Friction Slope Method=2
Unsteady Bridges Friction Slope Method=1
Global Log Level=0
CheckData=False
Run HTab=0
Run UNet=0
Run PostProcess=0
UNET Theta=0
UNET Theta Warmup=0
UNET ZTol=0
UNET ZSATol=0
UNET MxIter=0
UNET MaxInSteps=0
UNET DtIC=0
UNET DtMin=0
UNET MaxCRTS=0
UNET WFStab=0
UNET SFStab=0
UNET WFX=0
UNET SFX=0
UNET DSS MLevel=0
UNET DZMax Abort=0
UNET Convert EG Bridges=0
UNET Use Existing IB Tables=0
UNET Froude Limit=0
UNET Froude Power=0
Write IC File=0
Echo Input=False
Echo Output=False
Write Detailed=0

--- NP1.f01 (steady flow) ---

Flow Title=NFF Regression Equation
Program Version=4.00
Number of Profiles=1
Profile Names=P100yr
River Rch & RM=NP1,Main      ,11349.6
534.5604
River Rch & RM=NP1,Main      ,9678.8
548.2830
River Rch & RM=NP1,Main      ,9038
586.2853
River Rch & RM=NP1,Main      ,7501.2
636.3240
River Rch & RM=NP1,Main      ,5898.3
674.4451
River Rch & RM=NP1,Main      ,5011.6
741.5440
River Rch & RM=NP1,Main      ,97.8
803.8353
Boundary for River Rch & Prof#=NP1,Main      ,1
Up Type=0
Dn Type=3
Dn Slope=0.019524

--- NP1.g01 (geometry) ---

Geom Title=USGS 10m DEM
Program Version=4.10

River Reach=NP1             ,Main
Reach XY= 30
     1891554.666      284513.418     1891677.356      284643.794
     1891881.079      284685.591     1892984.224      285243.193
     1893411.307      285306.561     1893703.088      285536.498
     1893947.404      285548.531     1894055.911      285616.891
     1894295.711      285527.915     1894442.195      285613.635
     1894462.251      285722.674     1894622.317      285779.651
     1894724.313      285976.591     1895026.544      286149.542
     1895303.079      286458.402     1895853.871      286796.361
     1896267.282       286697.62     1896578.697      286530.519
     1897043.107       286387.29     1897138.593      286193.605
     1897356.692      286078.588     1897458.688      286088.353
     1897612.969      285850.887     1897912.247      285677.655
     1898119.496      285302.763     1898442.846      285035.836
     1899437.855      284780.845     1899931.562      284252.416
     1900395.173      283933.038     1900615.766      283517.952

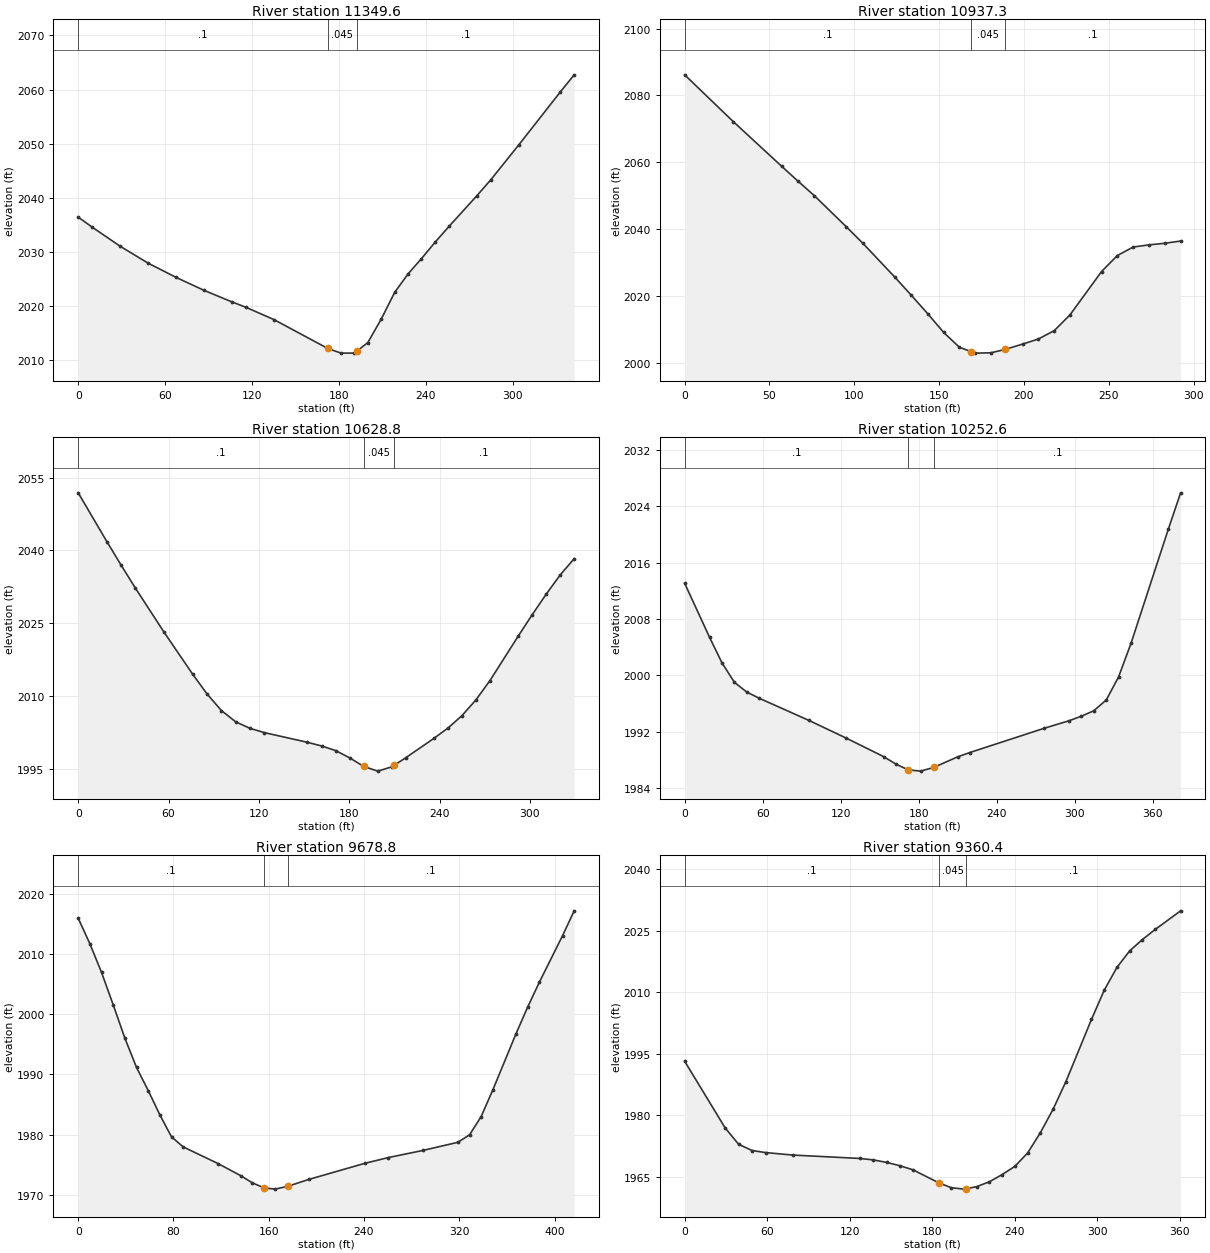
Type RM Length L Ch R = 1 ,11349.6 ,421.1,412.4,404.1
XS GIS Cut Line= 4
      1891434.64      284675.253      1891546.62      284599.732
     1891632.557      284545.045     1891700.265      284464.315
#Sta/Elev= 25
       0 2036.41     9.6 2034.57    28.9 2031.04    48.2 2027.91    67.5 2025.28
    86.8 2022.88   106.1 2020.74   115.8 2019.74   135.1 2017.47   172.2 2012.14
   181.4 2011.27   190.6 2011.28   192.2 2011.61   199.9 2013.22   209.2 2017.59
   218.4 2022.49   227.7 2025.93   236.9 2028.74   246.5 2031.83   256.1 2034.75
   275.2 2040.38   284.8 2043.33     304 2049.74   332.7 2059.54   342.3 2062.72
#Mann= 3 , 0 , 0
       0      .1       0   172.2    .045       0   192.2      .1       0
Bank Sta=172.2,192.2
XS Rating Curve= 0 ,0
Exp/Cntr=0.3,0.1

Type RM Length L Ch R = 1 ,10937.3 ,313.8,308.5,302.5
XS GIS Cut Line= 3
     1891842.626      284859.281     1891941.585      284742.961
      1892028.39      284633.586
#Sta/Elev= 26
       0 2086.15    28.6 2072.17    57.3 2058.72    66.8 2054.33    76.4    2050
    95.4 2040.62     105 2035.76   124.1 2025.49   133.6 2020.18   143.2 2014.71
   152.7 2009.04     162 2004.59   168.9  2003.3   171.3 2002.85   180.6 2002.95
   188.9 2003.96   199.3 2005.56   208.6 2007.09   217.9 2009.58   227.2 2014.32
   245.8 2027.28   255.1 2032.06   264.4  2034.6   273.7 2035.25     283 2035.73
   292.4  2036.4
#Mann= 3 , 0 , 0
       0      .1       0   168.9    .045       0   188.9      .1       0
Bank Sta=168.9,188.9
XS Rating Curve= 0 ,0
Exp/Cntr=0.3,0.1

Type RM Length L Ch R = 1 ,10628.8 ,376.9,376.2,375.1
XS GIS Cut Line= 3
     1892123.876      285057.197     1892203.738      284916.572
     1892276.654      284765.531
#Sta/Elev= 30
       0 2051.89      19 2041.84    28.5 2036.96      38 2032.22    57.1 2023.09
    76.1 2014.43    85.6 2010.37    95.1 2006.97   104.6 2004.63   114.2 2003.28
   123.7  2002.4   152.2 2000.41   161.7 1999.65     171  1998.7   180.4 1997.18
   189.7 1995.42     199 1994.46   208.3 1995.35   209.7 1995.63   217.6 1997.23
   236.3 2001.23   245.6 2003.35   254.9 2005.92   264.2 2009.17   273.5 2013.16
   292.2  2022.3   301.5 2026.72   310.8 2030.96   320.1 2034.94   329.4  2038.3
#Mann= 3 , 0 , 0
       0      .1       0   189.7    .045       0   209.7      .1       0
Bank Sta=189.7,209.7
XS Rating Curve= 0 ,0
Exp/Cntr=0.3,0.1

Type RM Length L Ch R = 1 ,10252.6 ,579.3,573.8,567.9
XS GIS Cut Line= 4
     1892467.626      285199.559     1892544.015      285078.031
      1892582.21      284991.225     1892616.932      284852.336
#Sta/Elev= 24
       0 2013.06    19.1 2005.42    28.7 2001.78    38.3 1999.01    47.8 1997.64
    57.4 1996.76    95.7 1993.61   124.4  1991.1     153 1988.49   162.5 1987.43
   171.8 1986.62   181.5 1986.43   191.8 1986.97   209.9 1988.45   219.4 1989.07
   276.6 1992.51   295.6 1993.57   305.2 1994.22   314.7 1994.99   324.3 1996.52
   333.8  1999.8   343.4 2004.58     372 2020.71   381.5 2025.89
#Mann= 3 , 0 , 0
       0      .1       0   171.8    .045       0   191.8      .1       0
Bank Sta=171.8,191.8
XS Rating Curve= 0 ,0
Exp/Cntr=0.3,0.1

Type RM Length L Ch R = 1 ,9678.8  ,302.3,318.4,332.9
XS GIS Cut Line= 4
     1893017.974      285407.892     1893070.057      285291.572
     1893092.626      285180.461     1893129.085      285008.586
#Sta/Elev= 29
       0 2015.95     9.8 2011.71    19.6 2006.95    29.4 2001.56    39.2 1996.02
      49 1991.16    58.8 1987.33    68.6 1983.28    78.4 1979.63    88.2 1977.97
   117.6 1975.19   136.9 1973.15   146.3    1972   155.9 1971.18   165.2 1970.96
   175.9 1971.42   193.6 1972.57   240.8 1975.25   260.4  1976.2   289.6 1977.39
   318.9 1978.74   328.7 1979.99   338.4 1983.01   348.2 1987.44   367.7 1996.78
   377.5 2001.21   387.2  2005.3   406.8 2013.07   416.5 2017.18
#Mann= 3 , 0 , 0
       0      .1       0   155.9    .045       0   175.9      .1       0
Bank Sta=155.9,175.9
XS Rating Curve= 0 ,0
Exp/Cntr=0.3,0.1

Type RM Length L Ch R = 1 ,9360.4  ,328,322.4,316.4
XS GIS Cut Line= 4
     1893264.501      285451.295      1893363.46      285329.767
     1893432.904      285255.114     1893502.349      285180.461
#Sta/Elev= 30
       0 1993.19    29.4 1976.98    39.2 1972.98      49 1971.46    58.8 1970.96
    78.4 1970.36   127.3 1969.53   137.1 1969.18   146.9 1968.56   156.7 1967.74
     166 1966.76   184.7 1963.61   193.8 1962.41   203.1 1962.06   204.7 1962.16
   212.3 1962.66   221.6 1963.86   230.9 1965.62   240.1 1967.61   249.4 1970.88
   258.7 1975.84     268  1981.6   277.2 1988.24   295.8  2003.4     305 2010.45
   314.3 2016.05   323.6 2020.09   332.8 2022.82   342.1 2025.28   360.6 2029.82
#Mann= 3 , 0 , 0
       0      .1       0   184.7    .045       0   204.7      .1       0
Bank Sta=184.7,204.7
XS Rating Curve= 0 ,0
Exp/Cntr=0.3,0.1

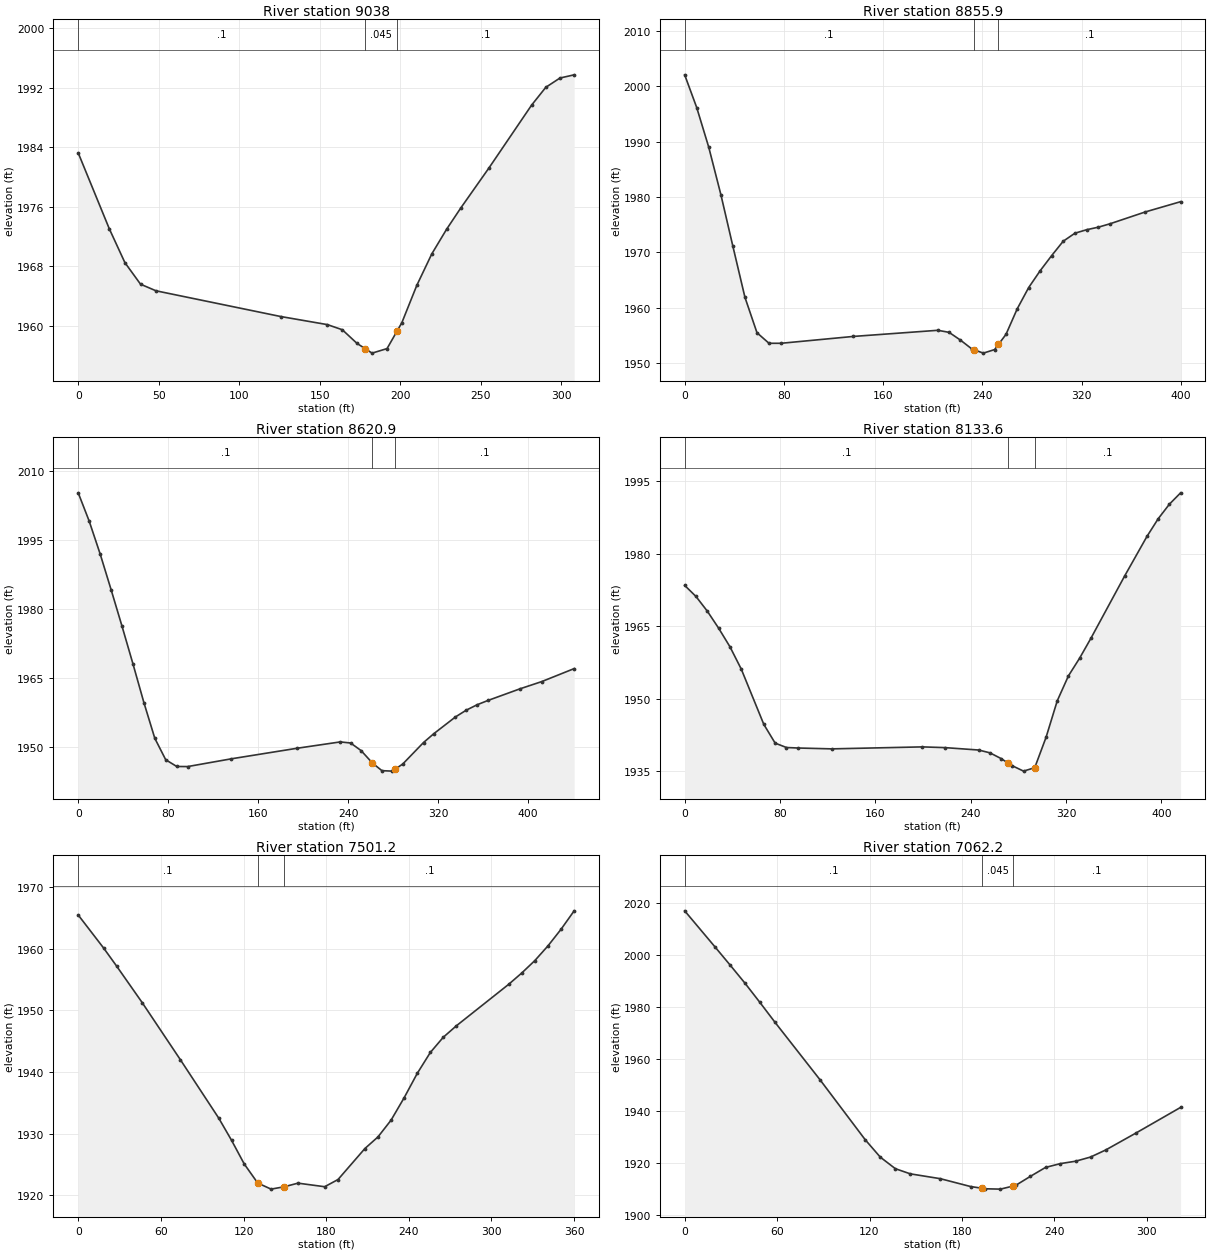
Type RM Length L Ch R = 1 ,9038    ,188.1,182.2,176
XS GIS Cut Line= 4
     1893509.293      285638.795     1893618.668       285529.42
     1893658.599       285466.92     1893693.321      285395.739
#Sta/Elev= 23
       0 1983.25    19.3 1973.04      29 1968.48    38.7 1965.58    48.3 1964.69
   125.7 1961.23   154.7 1960.14     164 1959.45   173.2  1957.6   178.1 1956.92
   182.5  1956.3   191.8 1956.91   198.1  1959.3     201  1960.4   210.3 1965.43
   219.6 1969.66   228.8 1972.98   237.6 1975.84   255.2 1981.26   281.6 1989.69
   290.4 1992.08   299.2 1993.33     308 1993.76
#Mann= 3 , 0 , 0
       0      .1       0   178.1    .045       0   198.1      .1       0
Bank Sta=178.1,198.1
XS Rating Curve= 0 ,0
Exp/Cntr=0.3,0.1

Type RM Length L Ch R = 1 ,8855.9  ,228.4,235,240.7
XS GIS Cut Line= 4
     1893762.765      285793.309     1893795.751       285591.92
     1893825.265      285505.114     1893823.529      285400.947
#Sta/Elev= 30
       0  2002.1     9.7 1996.18    19.4 1989.01    29.2 1980.41    38.9 1971.05
    48.6 1961.84    58.3 1955.44      68 1953.53    77.7 1953.53     136 1954.77
   204.1 1955.88   213.2 1955.51   222.4  1954.1   231.6  1952.5     233 1952.39
   240.8 1951.75   249.9 1952.39     253 1953.32   259.1 1955.15   268.2 1959.79
   277.4 1963.62   286.6 1966.64   295.8 1969.36   305.2 1971.99   314.7 1973.45
   324.2 1974.08   333.6 1974.54   343.1 1975.16   371.5  1977.3   399.9 1979.15
#Mann= 3 , 0 , 0
       0      .1       0     233    .045       0     253      .1       0
#XS Ineff= 2 , 0
          204.36 1955.84
Permanent Ineff=
       F       F
Bank Sta=233,253
XS Rating Curve= 0 ,0
Exp/Cntr=0.3,0.1

Type RM Length L Ch R = 1 ,8620.9  ,482.9,487.2,487.6
XS GIS Cut Line= 4
     1893967.192      285872.576     1893989.328       285649.92
     1894038.807      285571.795     1894063.113      285449.559
#Sta/Elev= 30
       0 2005.28     9.7 1999.17    19.5    1992    29.2 1984.26    38.9 1976.33
    48.6 1968.17    58.4 1959.69    68.1 1951.93    77.8 1947.27    87.6 1945.81
    97.3 1945.79   136.2 1947.48   194.6 1949.77     233 1951.15   242.2 1950.91
   251.5 1949.26   261.6 1946.55     270  1944.9   279.2  1944.8   281.6  1945.2
   288.5 1946.34     307 1951.02   316.2 1952.95   335.4 1956.58     345 1958.05
   354.6 1959.22   364.2 1960.15   392.9  1962.7   412.1 1964.26   440.9 1967.08
#Mann= 3 , 0 , 0
       0      .1       0   261.6    .045       0   281.6      .1       0
#XS Ineff= 2 , 0
          233.06 1951.08
Permanent Ineff=
       F       F
Bank Sta=261.6,281.6
XS Rating Curve= 0 ,0
Exp/Cntr=0.3,0.1

Type RM Length L Ch R = 1 ,8133.6  ,630.1,632.5,635.1
XS GIS Cut Line= 3
     1894281.863      285848.864      1894403.39      285656.156
     1894504.953      285497.576
#Sta/Elev= 30
       0 1973.48     9.5 1971.18      19 1968.14    28.5 1964.61      38 1960.76
    47.5 1956.13    66.4 1944.69    75.9 1940.81    85.4  1939.9    94.9  1939.8
   123.4 1939.62   199.4 1940.03   218.3 1939.88   246.7 1939.38   256.1  1938.8
   265.5 1937.61   271.6 1936.64   274.9 1936.12   284.3 1935.01   293.7 1935.72
   303.2 1942.01   312.6 1949.58     322 1954.75   331.4 1958.42   340.8 1962.51
   369.1 1975.41   387.9 1983.64   397.3 1987.29   406.7  1990.3   416.1 1992.65
#Mann= 3 , 0 , 0
       0      .1       0   271.6    .045       0   293.7      .1       0
Bank Sta=271.6,293.7
XS Rating Curve= 0 ,0
Exp/Cntr=0.3,0.1

Type RM Length L Ch R = 1 ,7501.2  ,438.9,439,440.9
XS GIS Cut Line= 4
     1894719.363       286123.17      1894809.64      286043.309
     1894865.196        285975.6     1894960.682      285857.545
#Sta/Elev= 28
       0 1965.49    18.5 1960.11    27.8 1957.22    46.4 1951.28    74.2 1941.98
     102 1932.51   111.3 1928.91   120.5 1925.07   130.3 1921.97     140 1920.98
   149.7 1921.37   159.5 1921.95   178.9 1921.37   188.6 1922.54   208.1 1927.57
   217.6 1929.46   227.1 1932.18   236.6 1935.82   246.1 1939.77   255.6 1943.17
     265 1945.64   274.5  1947.5   312.5 1954.24     322 1956.08   331.5  1958.1
     341 1960.48   350.5 1963.18     360 1966.17
#Mann= 3 , 0 , 0
       0      .1       0   130.3    .045       0   149.7      .1       0
Bank Sta=130.3,149.7
XS Rating Curve= 0 ,0
Exp/Cntr=0.3,0.1

Type RM Length L Ch R = 1 ,7062.2  ,389.6,387.1,384.4
XS GIS Cut Line= 3
     1895004.085       286435.67      1895122.14      286333.239
      1895238.46      286215.184
#Sta/Elev= 26
       0 2016.92    19.5 2003.19    29.3 1996.23    39.1 1989.16    48.8 1981.77
    58.6 1974.13    87.9    1952   117.2    1929     127  1922.3   136.8 1917.86
   146.5 1915.88     166 1914.02   185.6 1911.01   193.3 1910.32   195.3 1910.14
     205 1910.01   213.3  1911.2   214.8 1911.41   224.5 1914.93   234.3 1918.35
     244 1919.82   253.8 1920.73   263.5 1922.33   273.3 1925.03   292.8 1931.49
     322 1941.41
#Mann= 3 , 0 , 0
       0      .1       0   193.3    .045       0   213.3      .1       0
Bank Sta=193.3,213.3
XS Rating Curve= 0 ,0
Exp/Cntr=0.3,0.1

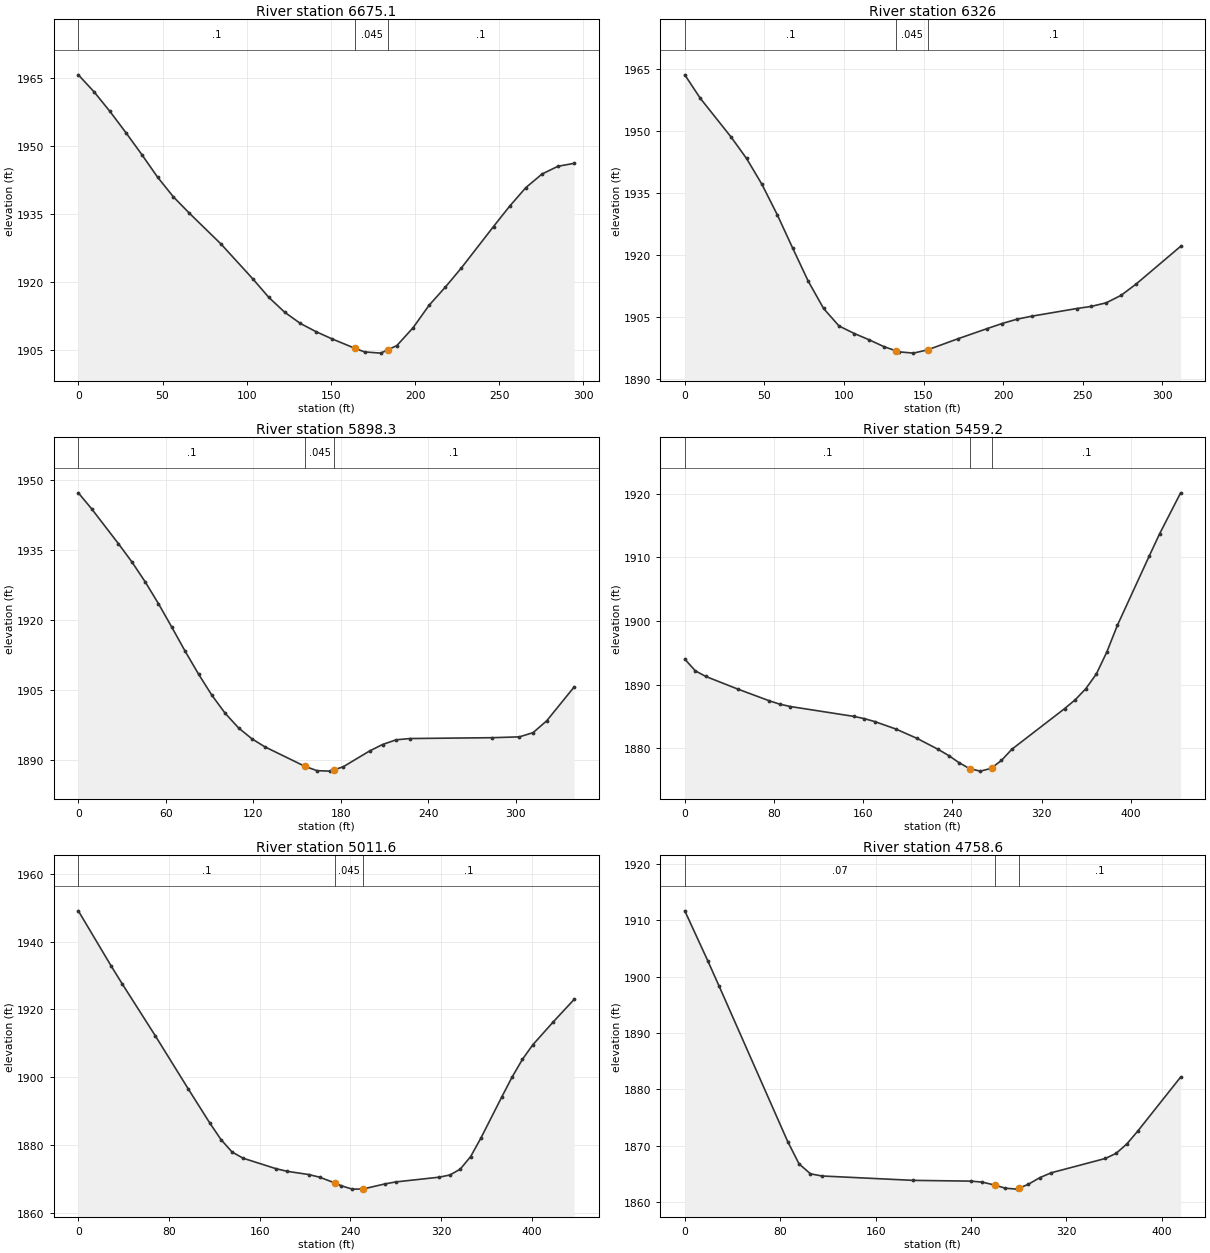
Type RM Length L Ch R = 1 ,6675.1  ,352.3,349.1,345.8
XS GIS Cut Line= 3
     1895344.363      286680.461     1895429.432      286567.614
     1895524.918      286447.822
#Sta/Elev= 30
       0 1965.77     9.4    1962    18.8 1957.69    28.3    1953    37.7 1948.19
    47.1 1943.19    56.5 1938.85      66 1935.24    84.8 1928.44   103.6 1920.79
   113.1 1916.71   122.5 1913.44   131.9 1910.94   141.3 1909.11   150.9 1907.51
   164.1 1905.49     170 1904.67   179.6  1904.4   184.1 1905.18   189.2 1906.07
   198.8 1909.99   208.3 1914.94   217.9 1918.92   227.5 1923.18   246.6 1932.32
   256.2 1936.81   265.8  1940.9   275.4 1943.89   284.9 1945.61   294.5 1946.25
#Mann= 3 , 0 , 0
       0      .1       0   164.1    .045       0   184.1      .1       0
Bank Sta=164.1,184.1
XS Rating Curve= 0 ,0
Exp/Cntr=0.3,0.1

Type RM Length L Ch R = 1 ,6326    ,445.8,427.8,409.6
XS GIS Cut Line= 4
     1895646.446      286866.225     1895710.682      286781.156
     1895754.085      286709.975     1895757.557      286588.447
#Sta/Elev= 28
       0 1963.49     9.7 1957.83    29.1 1948.43    38.8 1943.25    48.4 1937.04
    58.1 1929.64    67.8 1921.55    77.5 1913.61    87.2 1906.96    96.9 1902.72
   106.6 1900.89   115.9 1899.37   125.1 1897.73   132.6 1896.72   134.4 1896.48
   143.6 1896.16   152.6 1896.96   171.4 1899.61     190  1902.1   199.3 1903.32
   208.7 1904.37     218  1905.1   246.1 1906.94   255.4 1907.47   264.8 1908.34
   274.1 1910.14   283.5 1912.86   311.5    1922
#Mann= 3 , 0 , 0
       0      .1       0   132.6    .045       0   152.6      .1       0
Bank Sta=132.6,152.6
XS Rating Curve= 0 ,0
Exp/Cntr=0.3,0.1

Type RM Length L Ch R = 1 ,5898.3  ,443.5,439,433.9
XS GIS Cut Line= 4
     1896167.279      286895.739      1896144.71        286788.1
     1896127.349      286690.878     1896092.626      286564.142
#Sta/Elev= 28
       0 1947.15     9.2  1943.7    27.5 1936.26    36.7 1932.38    45.8 1928.12
      55  1923.4    64.2 1918.34    73.3 1913.22    82.5 1908.31    91.6 1903.81
   100.8 1899.91     110 1896.78     119 1894.49   127.9 1892.76   155.5 1888.56
   163.8 1887.64   172.8 1887.54   175.5 1887.82   181.8 1888.48   199.8 1891.85
   208.7 1893.24   218.1 1894.25   227.5 1894.52   283.8  1894.7   302.6 1894.88
     312 1895.78   321.4 1898.33   340.2 1905.57
#Mann= 3 , 0 , 0
       0      .1       0   155.5    .045       0   175.5      .1       0
Bank Sta=155.5,175.5
XS Rating Curve= 0 ,0
Exp/Cntr=0.3,0.1

Type RM Length L Ch R = 1 ,5459.2  ,452.2,447.6,443.3
XS GIS Cut Line= 3
     1896564.849      286812.406     1896545.751      286595.392
     1896464.154      286383.586
#Sta/Elev= 30
       0 1893.99     9.5 1892.15    18.9 1891.27    47.4  1889.3    75.8 1887.45
    85.2 1886.92    94.7 1886.55   151.6    1885     161 1884.65   170.5 1884.18
   189.4 1883.01   208.4 1881.54   227.3 1879.82   236.8 1878.84   246.2 1877.71
   255.6 1876.78   265.1  1876.4   274.6 1876.82   275.6 1876.95     284 1878.07
   293.5 1879.85   340.8 1886.23   350.3 1887.62   359.7 1889.34   369.2 1891.66
   378.6 1895.12   388.1 1899.32   416.5 1910.14   425.9 1913.67   444.8 1920.12
#Mann= 3 , 0 , 0
       0      .1       0   255.6    .045       0   275.6      .1       0
Bank Sta=255.6,275.6
XS Rating Curve= 0 ,0
Exp/Cntr=0.3,0.1

Type RM Length L Ch R = 1 ,5011.6  ,268.1,253,237.3
XS GIS Cut Line= 4
     1897024.918       286654.42     1896976.307       286466.92
     1896906.863      286352.336     1896835.682      286269.003
#Sta/Elev= 30
       0 1949.11      29 1932.81    38.7 1927.56    67.8 1912.28    96.8 1896.63
   116.2 1886.35   125.9 1881.56   135.6 1877.93   145.3  1876.1   174.3 1873.01
     184 1872.24   203.3 1871.27   212.8 1870.49   226.5 1868.76     232 1867.95
   241.6 1866.97   251.1 1867.01   270.3  1868.5   279.8 1869.09   318.1 1870.49
   327.7 1871.14   336.8 1872.86     346 1876.58   355.1 1882.08   373.4 1894.14
   382.5 1900.01   391.6 1905.24   400.8 1909.56     419 1916.38   437.3 1922.98
#Mann= 3 , 0 , 0
       0      .1       0   226.5    .045       0   251.1      .1       0
Bank Sta=226.5,251.1
XS Rating Curve= 0 ,0
Exp/Cntr=0.3,0.1

Type RM Length L Ch R = 1 ,4758.6  ,277.6,288.4,299
XS GIS Cut Line= 4
     1897339.154      286406.156     1897188.113        286288.1
     1897073.529      286237.753     1896981.515      286201.295
#Sta/Elev= 22
       0 1911.65    19.2 1902.83    28.8  1898.3    86.3 1870.77    95.8 1866.82
   105.4 1865.05     115 1864.67   191.7 1863.89   239.8 1863.76   249.5 1863.58
   259.9 1863.06   268.7 1862.51   278.4 1862.34   279.9 1862.47     288 1863.19
   297.6 1864.36   307.2 1865.23   352.8 1867.78   361.8 1868.69   370.8 1870.37
   379.8 1872.61   415.8 1882.19
#Mann= 3 , 0 , 0
       0     .07       0   259.9    .045       0   279.9      .1       0
Bank Sta=259.9,279.9
XS Rating Curve= 0 ,0
Exp/Cntr=0.3,0.1

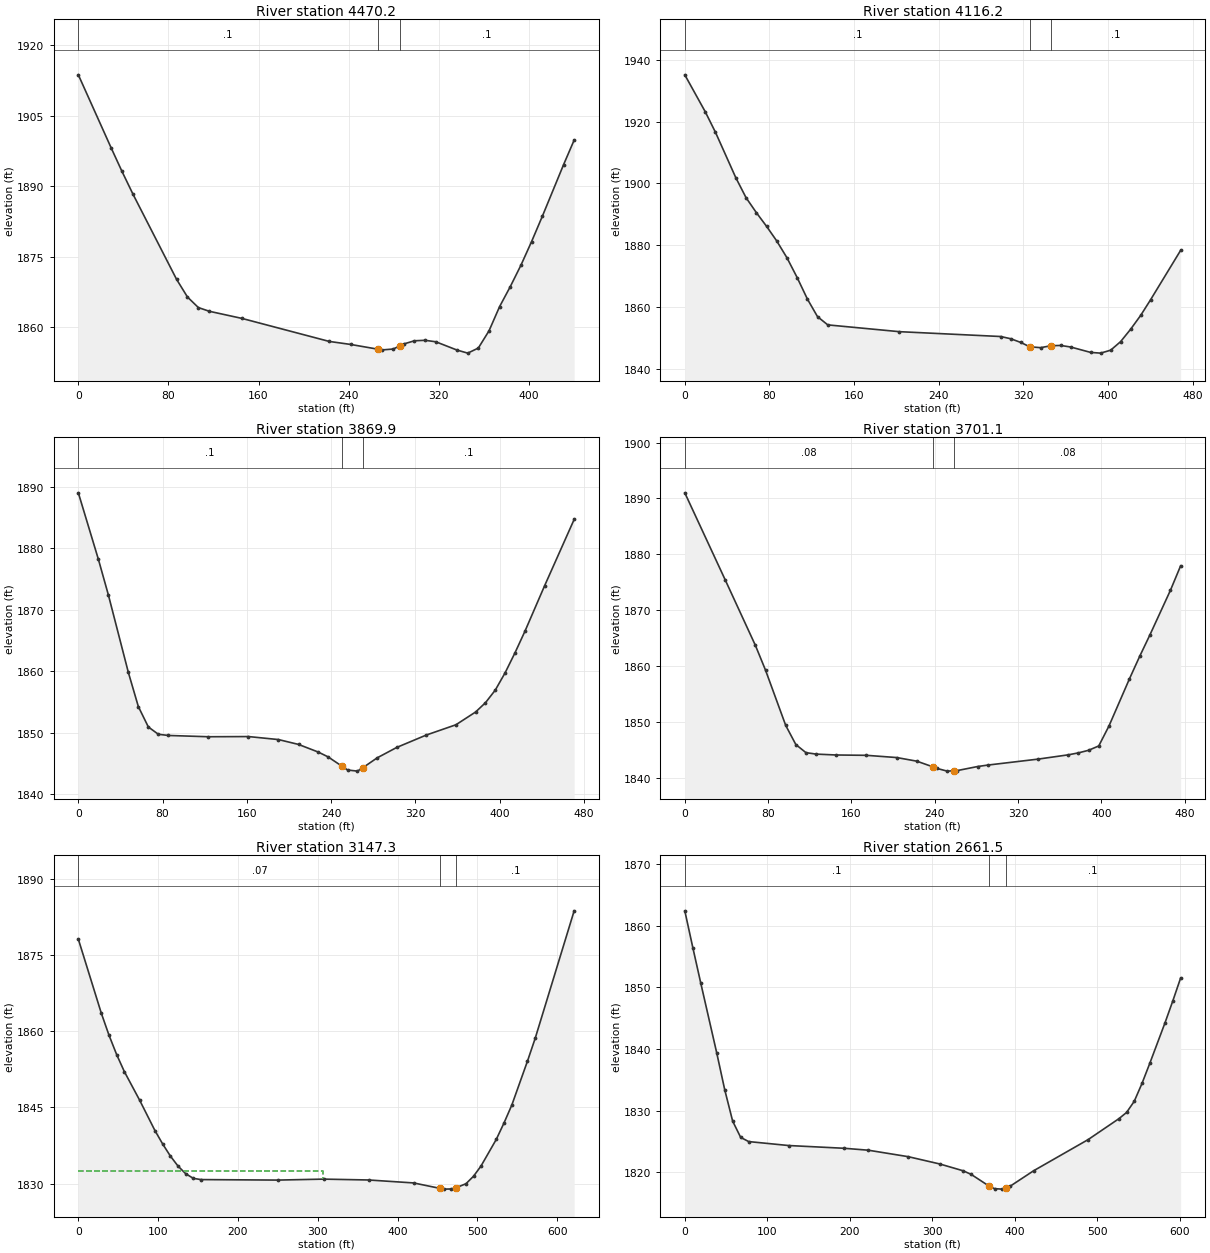
Type RM Length L Ch R = 1 ,4470.2  ,351.5,354,356.2
XS GIS Cut Line= 3
     1897472.835      286329.767     1897370.404       286131.85
     1897222.835      285972.128
#Sta/Elev= 30
       0 1913.68    29.1 1898.15    38.8  1893.1    48.4 1888.33    87.2 1870.16
    96.9 1866.38   106.6 1864.13   116.3 1863.34   145.3 1861.82   222.8 1856.92
   241.8 1856.28   265.7 1855.28   270.1 1855.12   279.6  1855.3   285.7    1856
     289 1856.38   298.5 1857.06   307.9 1857.16   317.4 1856.85   336.3 1855.08
   345.8 1854.43   355.2 1855.51   364.7 1859.18   374.1 1864.34   383.6  1868.6
     393 1873.13   402.5 1878.18     412 1883.54   430.9 1894.55   440.3 1899.79
#Mann= 3 , 0 , 0
       0      .1       0   265.7    .045       0   285.7      .1       0
Bank Sta=265.7,285.7
XS Rating Curve= 0 ,0
Exp/Cntr=0.3,0.1

Type RM Length L Ch R = 1 ,4116.2  ,238.3,246.3,253.5
XS GIS Cut Line= 3
     1897729.779      286203.031     1897608.251      285961.711
      1897488.46      285803.725
#Sta/Elev= 30
       0 1935.11    19.3 1923.19      29 1916.52    48.2 1901.85    57.9 1895.38
    67.6 1890.57    77.2 1886.16    86.8 1881.44    96.5 1875.98   106.2 1869.55
   115.8 1862.65   125.4 1856.93   135.1 1854.27   202.6 1852.08   298.5 1850.51
     308 1849.79   317.4  1848.6   326.1 1847.17   336.3 1846.91   346.1 1847.54
   355.2 1847.62   364.6 1847.12   383.5 1845.37   392.9 1845.14   402.4 1846.09
   411.8 1848.86   421.2 1852.84   430.7 1857.31   440.1 1862.39   468.5 1878.36
#Mann= 3 , 0 , 0
       0      .1       0   326.1    .045       0   346.1      .1       0
Bank Sta=326.1,346.1
XS Rating Curve= 0 ,0
Exp/Cntr=0.3,0.1

Type RM Length L Ch R = 1 ,3869.9  ,178.4,168.8,158.9
XS GIS Cut Line= 4
     1897882.557      285999.906     1897780.126      285817.614
     1897743.668      285711.711     1897639.501      285604.072
#Sta/Elev= 30
       0 1889.04      19 1878.24    28.5 1872.43    47.5 1859.79      57 1854.22
    66.5  1850.9      76 1849.71    85.5 1849.52   123.6 1849.31   161.6 1849.34
   190.1 1848.85   209.1 1848.06   227.8 1846.82   237.1 1846.04   250.4 1844.51
   255.8 1843.89   265.1 1843.71   270.4 1844.29   283.8 1845.87   302.4 1847.57
   330.5 1849.59   358.6 1851.26   377.3 1853.34   386.6 1854.84     396 1856.91
   405.4 1859.75   414.7 1862.98   424.1 1866.47   442.8 1873.89   470.9 1884.71
#Mann= 3 , 0 , 0
       0      .1       0   250.4    .045       0   270.4      .1       0
Bank Sta=250.4,270.4
XS Rating Curve= 0 ,0
Exp/Cntr=0.3,0.1

Type RM Length L Ch R = 1 ,3701.1  ,560.9,553.8,546
XS GIS Cut Line= 3
     1898070.057      285869.697     1897814.849      285578.031
     1897750.613      285517.267
#Sta/Elev= 30
       0 1890.99    38.8  1875.4    67.8 1863.66    77.5 1859.23    96.9 1849.33
   106.6 1845.91   116.3 1844.46     126  1844.2   145.3 1844.04   174.4 1843.98
   203.5 1843.58   222.8 1842.93   238.7 1841.88   242.2 1841.63   251.9 1841.15
   258.7 1841.22   261.6 1841.25     281 1841.97   290.7 1842.23   339.1  1843.3
   368.2 1844.07   377.9 1844.42   387.6 1844.88   397.4 1845.66   407.2 1849.23
   426.9 1857.69   436.7 1861.71   446.5 1865.54   466.2 1873.53     476 1877.92
#Mann= 3 , 0 , 0
       0     .08       0   238.7    .045       0   258.7     .08       0
Bank Sta=238.7,258.7
XS Rating Curve= 0 ,0
Exp/Cntr=0.3,0.1

Type RM Length L Ch R = 1 ,3147.3  ,471.3,485.7,499.2
XS GIS Cut Line= 4
     1898566.585      285527.684     1898333.946      285312.406
     1898169.015      285204.767     1898085.682      285137.059
#Sta/Elev= 30
       0 1878.14    28.8 1863.56    38.4 1859.24      48 1855.42    57.6 1852.08
    76.8 1846.44      96 1840.45   105.6 1837.83   115.3 1835.44   124.9 1833.46
   134.5 1831.96   144.1 1831.04   153.7  1830.8   249.7  1830.7   307.4 1830.89
   363.8 1830.72   420.1 1830.14   453.7 1829.05   457.6 1828.92     467 1828.95
   473.7 1829.21   485.8 1829.99   495.2 1831.46   504.5 1833.45   523.7 1838.71
   533.4 1841.95   543.2 1845.48   562.7 1854.08   572.5 1858.63   621.3 1883.72
#Mann= 3 , 0 , 0
       0     .07       0   453.7    .045       0   473.7      .1       0
#XS Ineff= 2 , 0
          306.63 1832.43
Permanent Ineff=
       F       F
Bank Sta=453.7,473.7
XS Rating Curve= 0 ,0
Exp/Cntr=0.3,0.1

Type RM Length L Ch R = 1 ,2661.5  ,403.2,398.8,394.2
XS GIS Cut Line= 4
     1898748.876      285354.072     1898649.918      285071.086
     1898578.738      284926.989     1898505.821      284807.197
#Sta/Elev= 30
       0  1862.4     9.7 1856.45    19.3 1850.71    38.7 1839.36    48.4 1833.38
      58  1828.3    67.7 1825.67    77.4 1824.99   125.7 1824.35   193.4  1823.9
   222.4 1823.59   270.8 1822.54   309.2 1821.35   337.6 1820.24   347.1 1819.66
   368.6 1817.78   375.4 1817.35   384.9 1817.28   388.6 1817.47   394.3 1817.76
   422.7 1820.26   488.6  1825.3     526  1828.7   535.3 1829.71   544.6 1831.52
     554 1834.42   563.4 1837.66     582 1844.29   591.4 1847.82   600.8 1851.51
#Mann= 3 , 0 , 0
       0      .1       0   368.6    .045       0   388.6      .1       0
Bank Sta=368.6,388.6
XS Rating Curve= 0 ,0
Exp/Cntr=0.3,0.1

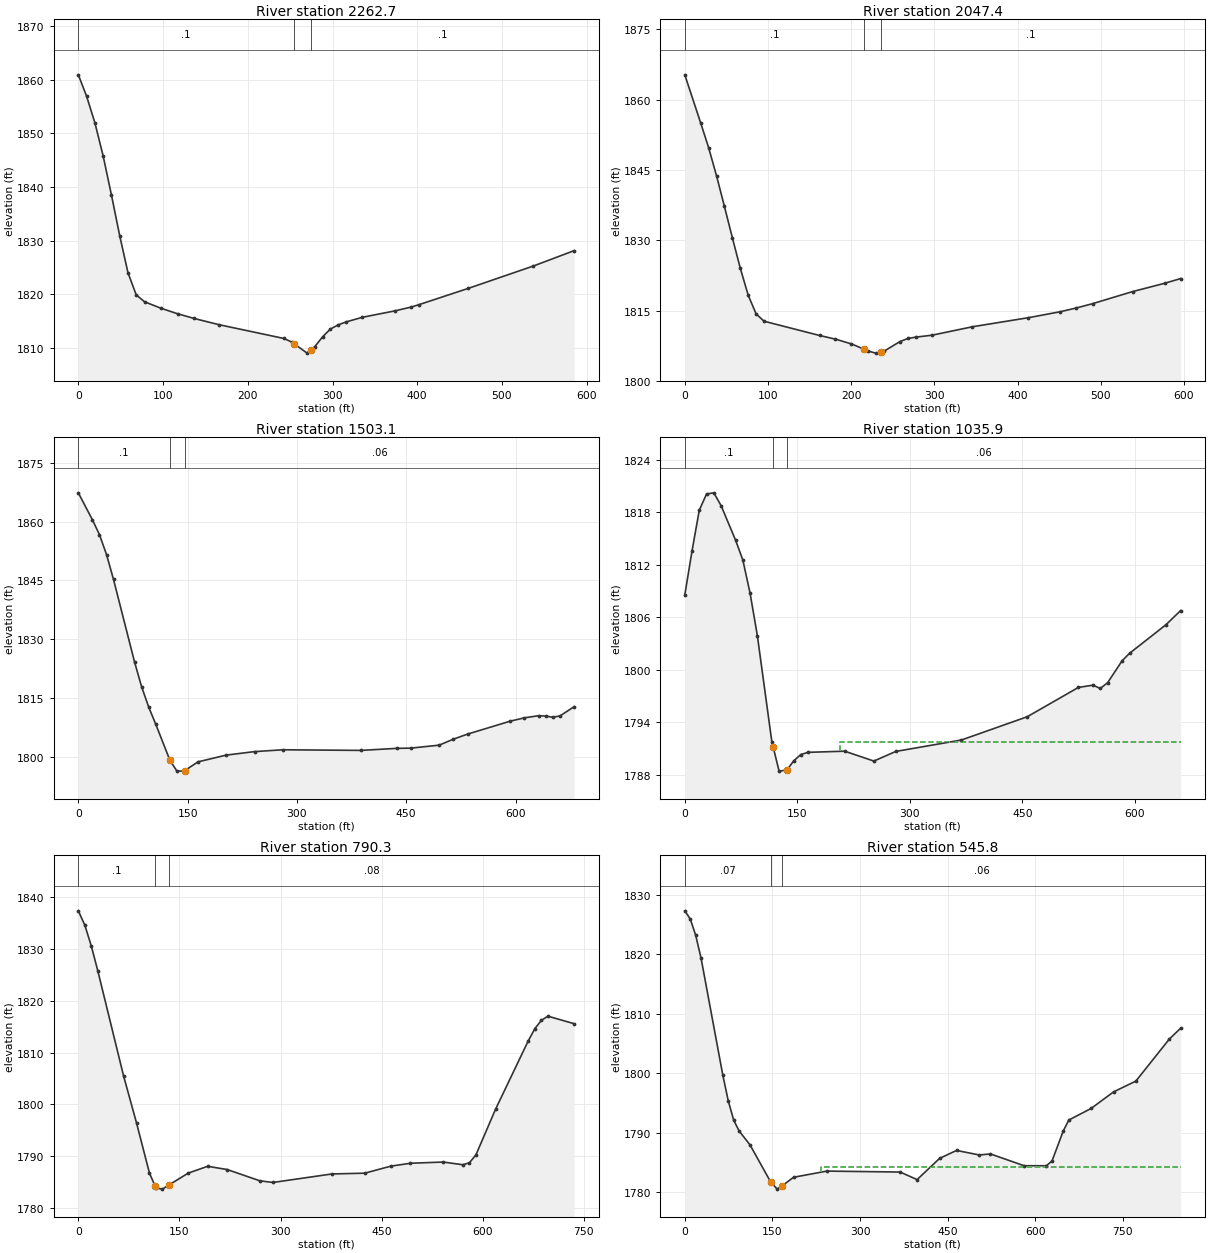
Type RM Length L Ch R = 1 ,2262.7  ,208.1,215.3,222.3
XS GIS Cut Line= 4
     1899132.557      285138.795     1899014.501      284947.822
      1898965.89       284881.85     1898788.807      284666.572
#Sta/Elev= 30
       0 1860.88     9.8 1856.87    19.5 1851.96    29.3 1845.76      39 1838.55
    48.8 1830.92    58.6    1824    68.3 1819.88    78.1 1818.59    97.6 1817.38
   117.1 1816.36   136.7 1815.48     166 1814.32   242.7 1811.75   251.8 1811.09
   254.3 1810.81     270 1809.02   274.3 1809.59   279.2 1810.25   288.2 1812.04
   297.4  1813.5   306.5 1814.27   316.1 1814.84   335.3  1815.7   373.8  1816.9
     393 1817.61   402.6 1818.08   460.3 1821.09   537.2 1825.26   585.2 1828.12
#Mann= 3 , 0 , 0
       0      .1       0   254.3    .045       0   274.3      .1       0
Bank Sta=254.3,274.3
XS Rating Curve= 0 ,0
Exp/Cntr=0.3,0.1

Type RM Length L Ch R = 1 ,2047.4  ,550.5,544.3,537.5
XS GIS Cut Line= 4
     1899287.071      285045.045     1899205.474      284883.586
     1899165.543      284774.211      1898934.64      284584.975
#Sta/Elev= 30
       0 1865.31      19 1855.08    28.6 1849.79    38.1 1843.78    47.6 1837.25
    57.1 1830.58    66.6  1824.1    76.2 1818.27    85.7  1814.3    95.2 1812.73
   161.9 1809.69   180.9 1808.91   200.3 1807.89   215.9 1806.72   219.7  1806.4
   229.4 1805.92   235.9 1806.17   239.1 1806.29   258.5 1808.38   268.2 1809.05
   277.9 1809.34   297.3 1809.75   345.5 1811.54   412.9 1813.48   451.4 1814.76
   470.7 1815.56     490 1816.47   538.1 1819.05   576.6 1820.82   595.9 1821.83
#Mann= 3 , 0 , 0
       0      .1       0   215.9    .045       0   235.9      .1       0
Bank Sta=215.9,235.9
XS Rating Curve= 0 ,0
Exp/Cntr=0.3,0.1

Type RM Length L Ch R = 1 ,1503.1  ,466.5,467.2,468
XS GIS Cut Line= 3
     1899695.057      284670.392     1899568.321      284487.753
     1899219.363      284190.878
#Sta/Elev= 30
       0 1867.36    19.3 1860.48      29 1856.69    38.7  1851.6    48.3 1845.24
    77.3 1824.08      87 1817.77    96.6 1812.66   106.3 1808.28   125.8 1799.05
   135.3 1796.35     145 1796.33   145.8 1796.43   164.3  1798.7     203 1800.42
   241.8 1801.31   280.8 1801.78     388 1801.62   436.8 1802.14   456.3  1802.2
   495.2 1802.96   514.7 1804.48   534.2 1805.78   592.7 1809.08   612.2 1809.93
   631.7 1810.48   641.5 1810.38   651.2 1810.09     661 1810.41   680.5 1812.78
#Mann= 3 , 0 , 0
       0      .1       0   125.8    .045       0   145.8     .06       0
Bank Sta=125.8,145.8
XS Rating Curve= 0 ,0
Exp/Cntr=0.3,0.1

Type RM Length L Ch R = 1 ,1035.9  ,244.8,245.6,246.1
XS GIS Cut Line= 3
      1900015.37      284347.909      1899925.96      284209.975
     1899557.904      283876.642
#Sta/Elev= 30
       0 1808.55     9.7 1813.62    19.3 1818.24      29  1820.1    38.7 1820.23
    48.4 1818.76    67.7 1814.81    77.4 1812.54      87 1808.76    96.7 1803.91
     116 1791.78  117.92 1791.12   125.7 1788.41   136.2 1788.54     145 1789.57
   154.7 1790.31   164.4 1790.56   213.1 1790.69     252 1789.56   281.2 1790.66
   368.8 1791.97   456.5 1794.63   524.6 1797.98   544.1 1798.24   553.8 1797.86
   563.6 1798.52     583 1801.04   592.8 1801.88   641.5 1805.16   660.9 1806.77
#Mann= 3 , 0 , 0
       0      .1       0  117.92    .045       0   136.2     .06       0
#XS Ineff= 2 , 0
                           206.3         1791.77
Permanent Ineff=
       F       F
Bank Sta=117.92,136.2
XS Rating Curve= 0 ,0
Exp/Cntr=0.3,0.1

Type RM Length L Ch R = 1 ,790.3   ,255.9,244.5,231.9
XS GIS Cut Line= 3
     1900222.835        284225.6      1900122.14      284062.406
     1899703.738      283715.184
#Sta/Elev= 30
       0  1837.4     9.6 1834.64    19.2 1830.63    28.8 1825.86    67.1 1805.52
    86.3 1796.44   105.5 1786.75   114.1 1784.19   115.1 1783.89   124.6 1783.65
   134.1 1784.43     163 1786.74   191.8 1788.06   220.9 1787.43   269.4 1785.25
   288.8 1784.94   376.2 1786.58   424.8 1786.73   463.6 1788.09   492.7 1788.65
   541.3 1788.88   570.4 1788.36   580.1 1788.74   589.8 1790.27     619 1799.11
   667.5 1812.31   677.2 1814.65   686.9 1816.25   696.6 1817.05   735.5  1815.6
#Mann= 3 , 0 , 0
       0      .1       0   114.1    .045       0   134.1     .08       0
#XS Ineff= 2 , 0
                          189.88         1787.87
Permanent Ineff=
       F       F
Bank Sta=114.1,134.1
XS Rating Curve= 0 ,0
Exp/Cntr=0.3,0.1

Type RM Length L Ch R = 1 ,545.8   ,209.5,213,216.5
XS GIS Cut Line= 5
     1900392.974      284112.753     1900380.821       283992.44
      1900300.96      283944.263     1900022.314      283752.857
     1899731.515       283694.35
#Sta/Elev= 30
       0 1827.26     9.3  1825.9    18.6 1823.18    27.9 1819.28    65.1 1799.65
    74.4 1795.34    83.7  1792.1      93 1790.28   111.6 1787.95   146.8 1781.75
   158.2 1780.51   166.8 1781.07   186.2  1782.5   243.2 1783.54   368.7 1783.38
   397.7 1782.11   436.3 1785.68   465.3 1787.01     504 1786.25   523.3 1786.42
     581 1784.44   619.2 1784.44   628.8 1785.26   647.9 1790.26   657.5 1792.12
   695.8 1794.07     734 1796.84   772.3 1798.66   829.7 1805.74   848.9 1807.53
#Mann= 3 , 0 , 0
       0     .07       0   146.8    .045       0   166.8     .06       0
#XS Ineff= 2 , 0
                          232.82         1784.27
Permanent Ineff=
       F       F
Bank Sta=146.8,166.8
XS Rating Curve= 0 ,0
Exp/Cntr=0.3,0.1

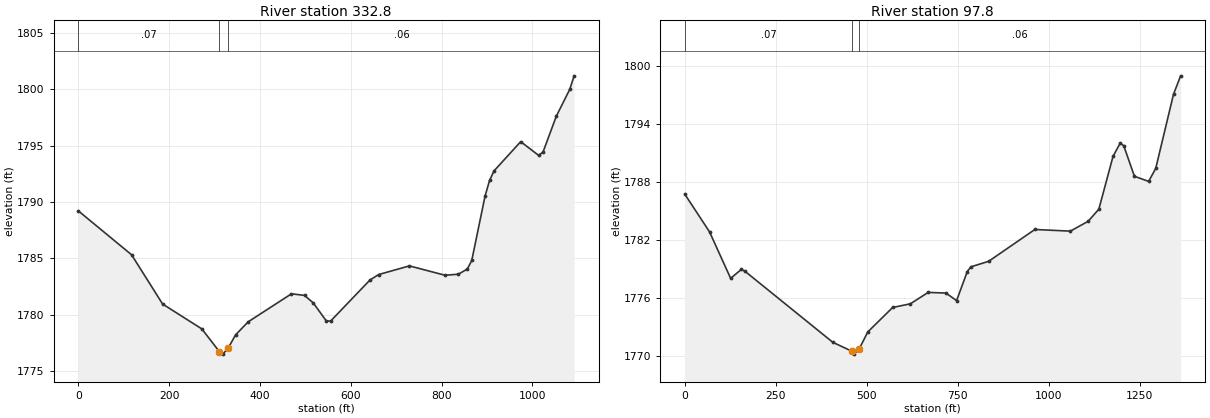
Type RM Length L Ch R = 1 ,332.8   ,238.3,235.1,232.5
XS GIS Cut Line= 5
     1900660.335      284046.781      1900519.71      283847.128
      1900403.39      283755.114      1900122.14       283631.85
     1899731.515      283666.572
#Sta/Elev= 30
       0 1789.21   117.2 1785.31   185.6 1780.93     272 1778.72   310.6  1776.7
   318.4 1776.48   330.6 1777.06   346.2 1778.19     374 1779.35   469.3 1781.84
   498.1  1781.7   517.3 1781.03   546.1 1779.43   555.6 1779.42     642 1783.06
   661.2 1783.55     729 1784.32   807.4 1783.49   836.8 1783.58   856.5 1784.04
   866.3  1784.8   895.7 1790.54   905.5 1791.91   915.3 1792.76   974.1 1795.36
  1013.3 1794.15  1023.1 1794.42  1052.5 1797.62    1082    1800  1091.8 1801.21
#Mann= 3 , 0 , 0
       0     .07       0   310.6    .045       0   330.6     .06       0
#XS Ineff= 2 , 0
                          456.54         1781.48
Permanent Ineff=
       F       F
Bank Sta=310.6,330.6
XS Rating Curve= 0 ,0
Exp/Cntr=0.3,0.1

Type RM Length L Ch R = 1 ,97.8    ,101.9,97.8,92.6
XS GIS Cut Line= 4
     1900741.932      284024.211      1900684.64      283670.045
     1900554.432      283588.447     1899705.474       283631.85
#Sta/Elev= 30
       0 1786.71    67.9 1782.82     126 1778.01   155.1 1778.93   164.8 1778.76
   406.8  1771.4   459.1 1770.48   464.4 1770.18   479.1 1770.71   502.8 1772.47
   571.1    1775   619.9 1775.38   668.8 1776.56   717.6 1776.49   746.9 1775.71
   776.2 1778.71     786  1779.2   834.9 1779.77   961.9 1783.06  1059.6 1782.89
  1108.5 1783.91  1137.8 1785.16  1176.8 1790.62  1196.4 1791.98  1206.2 1791.72
  1235.5 1788.56  1274.6 1788.03  1294.1 1789.37    1343 1797.04  1362.5 1798.94
#Mann= 3 , 0 , 0
       0     .07       0   459.1    .045       0   479.1     .06       0
Bank Sta=459.1,479.1
XS Rating Curve= 0 ,0
Exp/Cntr=0.3,0.1

Chan Stop Cuts=-1
Use User Specified Reach Order=0
Composite Channel Slope=5